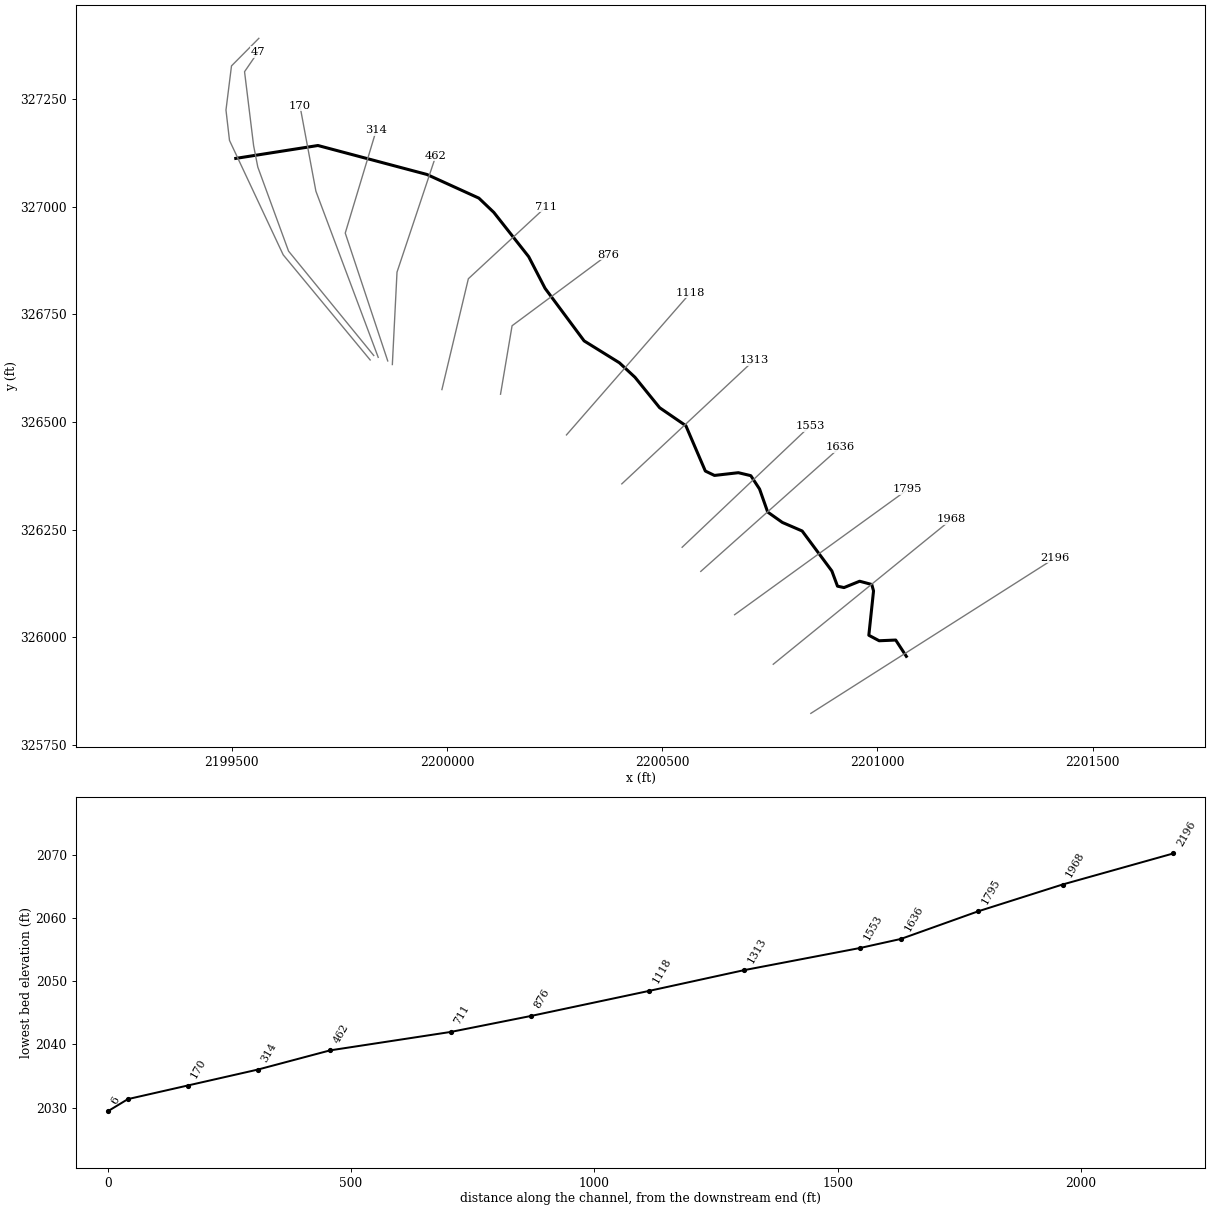
--- ANTNYCKT2_1.prj (project) ---

Proj Title=ANTNYCKT2_1
Current Plan=p01
Default Exp/Contr=0,0
English Units
Geom File=g02
Flow File=f02
Plan File=p01
BEGIN DESCRIPTION:
Stream Name- Anthony Creek Tributary 2.1
Flood Zone: Zone A
Greenbrier County, WV
County-Wide Study
WVDHSEM-2018-3, Flood Risk Project
HEC-RAS Version: 5.0.7
General Notes:
For the Hydrology regression was used.
END DESCRIPTION:
DSS Export Rating Curves= 0
DSS Export Rating Curve Sorted= 0
DSS Export Volume Flow Curves= 0
DXF OffsetX= 0
DXF OffsetY= 0
DXF ScaleX= 0
DXF ScaleY= 0

--- ANTNYCKT2_1.p01 (plan) ---

Plan Title=Floodplain
Program Version=5.07
Short Identifier=Floodplain
Geom File=g02
Flow File=f02
Subcritical Flow
K Sum by GR= 0
Std Step Tol= 0.01
Critical Tol= 0.01
Num of Std Step Trials= 20
Max Error Tol= 0.3
Flow Tol Ratio= 0.001
Split Flow NTrial= 30
Split Flow Tol= 0.02
Split Flow Ratio= 0.02
Log Output Level= 0
Friction Slope Method= 1
Unsteady Friction Slope Method= 2
Unsteady Bridges Friction Slope Method= 1
Parabolic Critical Depth
Global Vel Dist= 0 , 0 , 0
Global Log Level= 0
CheckData=True
Encroach Param=-1 ,0,0, 0
Mapping Interval=1HOUR
Computation Time Step Use Courant=        0
Computation Time Step Use Time Series=    0
Computation Time Step Count To Double=0
Computation Time Step Max Doubling=0
Computation Time Step Max Halving=0
Computation Time Step Residence Courant=0
Run HTab= 0
Run UNet= 0
Run Sediment= 0
Run PostProcess= 0
Run WQNet= 0
Run RASMapper= 0
UNET Theta= 0
UNET Theta Warmup= 0
UNET ZTol= 0
UNET ZSATol= 0
UNET MxIter= 0
UNET Max Iter WO Improvement= 0
UNET MaxInSteps= 0
UNET DtIC= 0
UNET DtMin= 0
UNET MaxCRTS= 0
UNET WFStab= 0
UNET SFStab= 0
UNET WFX= 1
UNET SFX= 1
UNET 1D Methodology=Finite Difference
UNET DSS MLevel= 1
UNET Pardiso=0
UNET DZMax Abort= 0
UNET Use Existing IB Tables= 0
UNET Froude Reduction=False
UNET Froude Limit= 0
UNET Froude Power= 0
UNET D1 Cores= 0
UNET D2 Coriolis=0
UNET D2 Cores= 0
UNET D2 Theta= 1
UNET D2 Theta Warmup= 1
UNET D2 Z Tol= 0.01
UNET D2 Volume Tol= 0.01
UNET D2 Max Iterations= 20
UNET D2 Equation= 0
UNET D2 RampUpFraction=0.1
UNET D2 TimeSlices= 1
UNET D2 BCVolumeCheck=0
UNET D1D2 MaxIter= 0
UNET D1D2 ZTol=0.01
UNET D1D2 QTol=0.1
UNET D1D2 MinQTol=1
Write IC File= 0
Write IC File at Fixed DateTime=0
Write IC File at Sim End=0
Echo Input=False
Echo Parameters=False
Echo Output=False
Write Detailed= 0
HDF Write Warmup=0
HDF Write Time Slices=0
HDF Flush=0
HDF Face Node Velocities=0
HDF Compression= 1
HDF Chunk Size= 1
HDF Spatial Parts= 1
HDF Use Max Rows=0
HDF Fixed Rows= 1
Calibration Method= 0
Calibration Iterations= 20
Calibration Max Change=0.05
Calibration Tolerance=0.2
Calibration Maximum=1.5
Calibration Minimum=0.5
Calibration Optimization Method= 1
WQ AD Non Conservative
WQ ULTIMATE=-1
WQ Max Comp Step=1HOUR
WQ Output Interval=15MIN
WQ Output Selected Increments= 0
WQ Output face flow=0
WQ Output face velocity=0
WQ Output face area=0
WQ Output face dispersion=0
WQ Output cell volume=0
WQ Output cell surface area=0
WQ Output cell continuity=0
WQ Output cumulative cell continuity=0
WQ Output face conc=0
WQ Output face dconc_dx=0
WQ Output face courant=0
WQ Output face peclet=0
WQ Output face adv mass=0
WQ Output face disp mass=0
WQ Output cell mass=0
WQ Output cell source sink temp=0
WQ Output nsm pathways=0
WQ Output nsm derived pathways=0
WQ Output MaxMinRange=-1
WQ Daily Max Min Mean=-1
WQ Daily Range=0
WQ Daily Time=0
WQ Create Restart=0
WQ Fixed Restart=0
WQ System Summary=0
WQ Write To DSS=0
WQ Use Fixed Temperature=0
Sorting and Armoring Iterations= 10
XS Update Threshold= 0.02
Bed Roughness Predictor= 0
Hydraulics Update Threshold= 0.02
Energy Slope Method= 1
Volume Change Method= 1
Sediment Retention Method= 0
XS Weighting Method= 0
Number of US Weighted Cross Sections= 1
Number of DS Weighted Cross Sections= 1
Upstream XS Weight=0
Main XS Weight=1
Downstream XS Weight=0
Number of DS XS's Weighted with US Boundary= 1
Upstream Boundary Weight= 1
Weight of XSs Associated with US Boundary= 0
Number of US XS's Weighted with DS Boundary= 1
Downstream Boundary Weight= 0.5
Weight of XSs Associated with DS Boundary= 0.5
Percentile Method= 0
Sediment Output Level= 3
Mass or Volume Output= 0
Output Increment Type= 1
Profile and TS Output Increment= 1
XS Output Flag= 0
XS Output Increment= 10
Write Gradation File= 0
Read Gradation Hotstart= 0
Write HDF5 File= 1
Write Binary Output= 1
Write DSS Sediment File= 0
SV Curve= 0
Specific Gage Flag= 0

--- ANTNYCKT2_1.f02 (steady flow) ---

Flow Title=ANTNYCKT2_1
Program Version=5.07
Number of Profiles= 6
Profile Names=f1p,f10p,f4p,f2p,f02p,f1pplus
River Rch & RM=ANTNYCKT2_1,Main            ,2196
     483     253     338     408     676     714
River Rch & RM=ANTNYCKT2_1,Main            ,1795
     635     337     447     538     885     939
Boundary for River Rch & Prof#=ANTNYCKT2_1,Main            , 1
Up Type= 0
Dn Type= 3
Dn Slope=0.016
Boundary for River Rch & Prof#=ANTNYCKT2_1,Main            , 2
Up Type= 0
Dn Type= 3
Dn Slope=0.016
Boundary for River Rch & Prof#=ANTNYCKT2_1,Main            , 3
Up Type= 0
Dn Type= 3
Dn Slope=0.016
Boundary for River Rch & Prof#=ANTNYCKT2_1,Main            , 4
Up Type= 0
Dn Type= 3
Dn Slope=0.016
Boundary for River Rch & Prof#=ANTNYCKT2_1,Main            , 5
Up Type= 0
Dn Type= 3
Dn Slope=0.016
Boundary for River Rch & Prof#=ANTNYCKT2_1,Main            , 6
Up Type= 0
Dn Type= 3
Dn Slope=0.016
DSS Import GetInterval= 0
DSS Import GetPeak= 0
DSS Import FillOption= 0

--- ANTNYCKT2_1.g02 (geometry) ---

Geom Title=ANTNYCKT2_1
Program Version=5.07

River Reach=ANTNYCKT2_1     ,Main
Reach XY= 30
     2201067.205      325955.693     2201042.492      325993.547
     2201004.038      325991.902     2200980.054      326004.657
        2200991.      326107.674     2200986.864      326122.601
     2200958.708      326130.152     2200922.424      326115.414
     2200907.288      326118.671     2200894.206      326153.932
     2200825.198      326246.858     2200779.192      326266.721
     2200745.127      326290.854     2200726.269      326344.306
      2200705.91      326375.356     2200677.045      326382.247
     2200621.535      326375.885     2200600.304      326386.089
     2200555.064      326491.416     2200494.094      326533.225
     2200436.955      326603.843       2200400.7      326637.542
     2200318.753      326688.396     2200228.097      326810.443
     2200190.033      326883.949     2200109.039      326986.826
     2200074.339       327019.96       2199953.6      327074.943
     2199700.531      327142.209     2199509.634      327112.254

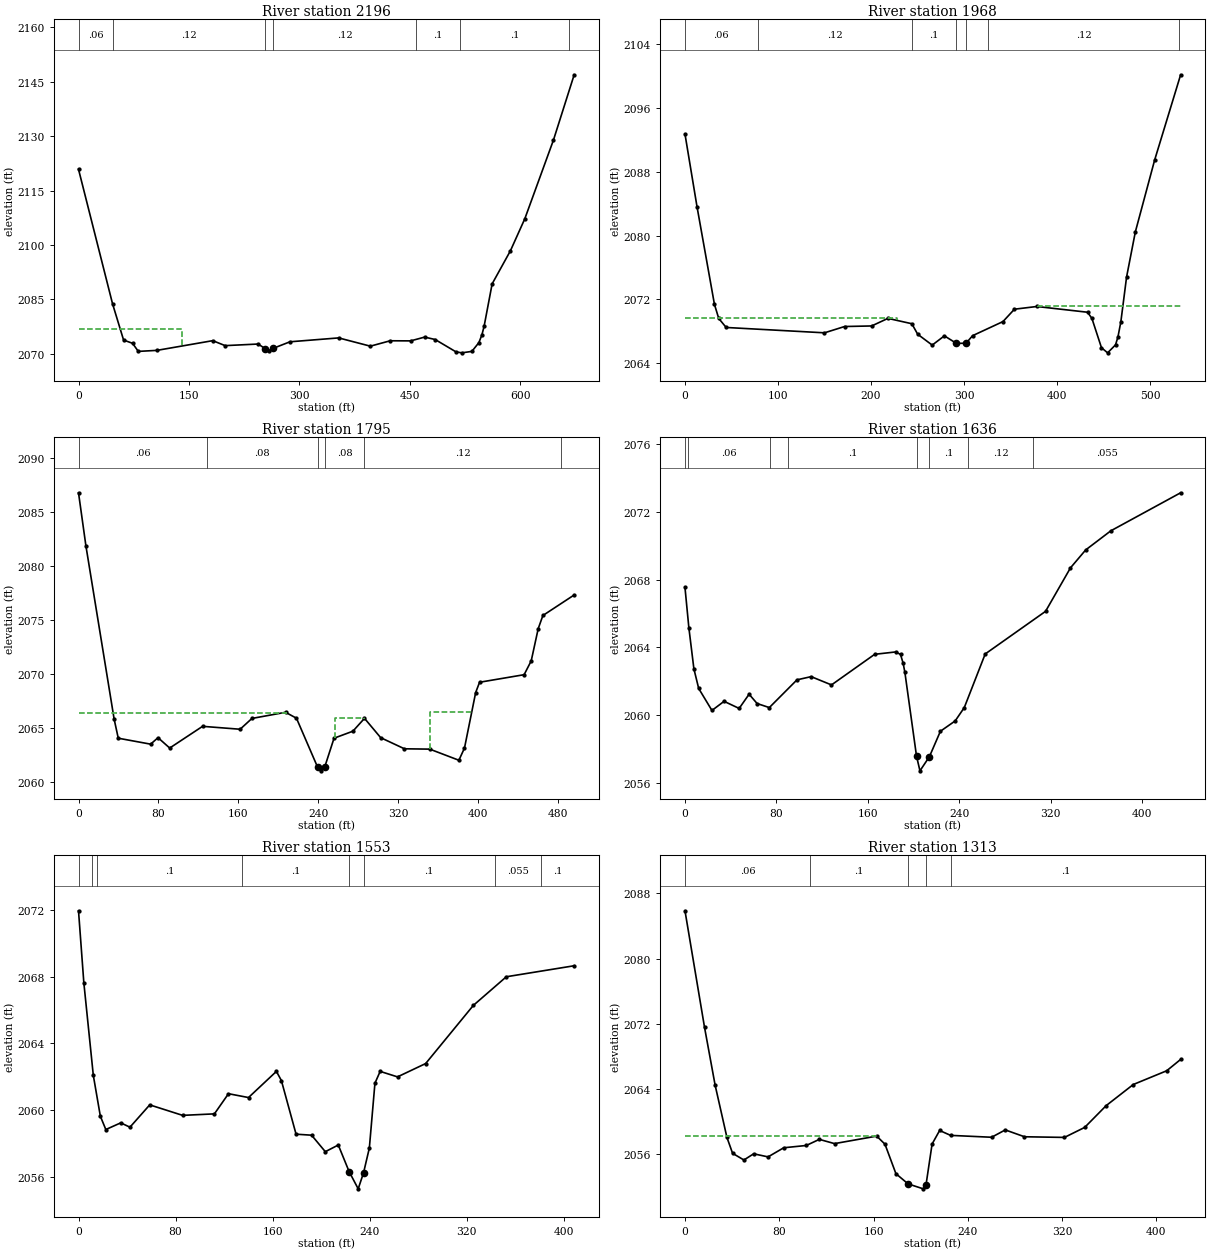
Type RM Length L Ch R = 1 ,2196    ,227.2,227.9,227.6
XS GIS Cut Line= 2
2200845.35667716325823.2244642952201413.30275915326184.504220062
#Sta/Elev= 30
       0 2120.87    46.2 2083.77    61.2 2073.75    73.4 2072.85    81.2 2070.62
   106.4  2070.9   182.3 2073.58   199.1 2072.21   243.9 2072.65   253.7 2071.36
   258.5 2070.84     2642071.434   287.2 2073.27   353.3 2074.34   396.3 2072.06
   423.3 2073.55     451 2073.52     470 2074.56   484.3  2073.9   512.6 2070.49
   520.5 2070.22   534.2 2070.62   543.7 2073.04   547.8 2075.17   550.8 2077.55
   561.7 2089.25   586.5 2098.37   606.1 2107.23     645 2128.95   673.1 2146.95
#Mann= 7 ,-1 , 0
       0     .06       0    46.2     .12       0   253.7    .045       0
     264     .12       0  458.36      .1       0  518.57      .1       0
  666.28      .1       0
#XS Ineff= 2 , 0
          140.56 2076.71  353.49          2074.3
Permanent Ineff=
       F       F
Bank Sta=253.7,264
XS Rating Curve= 0 ,0
Exp/Cntr(USF)=0,0
Exp/Cntr=0.3,0.1

Type RM Length L Ch R = 1 ,1968    ,173.1,173.5,173
XS GIS Cut Line= 2
2200758.09940692325937.3395564412201171.57965882326273.560522515
#Sta/Elev= 30
       0 2092.73      13 2083.58    31.7 2071.37    36.3 2069.61    44.3 2068.48
     150 2067.81   171.6  2068.6   200.7 2068.67   218.2 2069.62   243.9 2068.95
   250.2 2067.63   265.8 2066.27   278.9 2067.43   291.8 2066.49   302.2  2066.5
   309.2 2067.45   341.9 2069.22   354.2 2070.77   378.3 2071.11   432.8 2070.39
   437.5 2069.62   447.8 2065.94   454.4  2065.3   462.9  2066.3   465.5 2067.29
   468.6 2069.17   474.8 2074.82   484.2 2080.46     505 2089.49   532.9 2100.16
#Mann= 7 ,-1 , 0
       0     .06       0   78.07     .12       0   243.9      .1       0
   291.8    .045       0   302.2      .1       0  326.05     .12       0
  530.77      .1       0
#XS Ineff= 2 , 0
          227.91 2069.71  379.33         2071.12
Permanent Ineff=
       F       F
Bank Sta=291.8,302.2
XS Rating Curve= 0 ,0
Exp/Cntr(USF)=0,0
Exp/Cntr=0.3,0.1

Type RM Length L Ch R = 1 ,1795    ,159.3,158.8,159
XS GIS Cut Line= 2
2200668.34722603326052.3910098062201070.36708683326343.272274277
#Sta/Elev= 30
       0  2086.8     7.4 2081.89    35.7 2065.83    39.8 2064.08    72.2 2063.53
    79.6 2064.13    91.3 2063.17   124.2 2065.18   161.8 2064.91   173.6 2065.91
   207.3 2066.48   218.2 2065.93   239.3 2061.41   242.3 2061.06   246.5 2061.42
   255.8 2064.08   274.7 2064.73   286.3 2065.92   302.5 2064.13   326.3  2063.1
   351.6 2063.07   380.8 2062.04   386.4 2063.17   397.6 2068.31   401.5 2069.26
   446.1 2069.96   453.2 2071.24   460.2 2074.22   464.9 2075.44   496.2 2077.34
#Mann= 6 ,-1 , 0
       0     .06       0  128.53     .08       0   239.3    .045       0
   246.5     .08       0   286.3     .12       0   483.2    .055       0
#XS Ineff= 3 ,-1
       0  208.88 2066.41  256.51  286.15 2065.91  351.57  394.22  2066.5
Permanent Ineff=
       F       F       F
Bank Sta=239.3,246.5
XS Rating Curve= 0 ,0
Exp/Cntr(USF)=0,0
Exp/Cntr=0.3,0.1

Type RM Length L Ch R = 1 ,1636    ,82.2,83.2,82.8
XS GIS Cut Line= 2
2200589.73877229326152.9857360462200913.52206493326441.538722237
#Sta/Elev= 30
       0 2067.53     3.4 2065.15     7.8 2062.72      12 2061.56    23.6 2060.26
    34.2  2060.8    47.4 2060.38    56.1 2061.22    63.1 2060.67    73.8 2060.43
      98 2062.07   110.4 2062.26   128.2 2061.77     166 2063.58   184.4 2063.72
   188.6 2063.57   190.9 2063.05   192.4 2062.52   202.6 2057.56   205.6 2056.69
   213.9 2057.53   223.5 2059.03   236.4 2059.64   244.4 2060.43   262.7  2063.6
   315.5 2066.12   337.3 2068.69   350.6 2069.75   372.6 2070.88   433.7 2073.13
#Mann= 8 ,-1 , 0
       0      .1       0    2.46     .06       0   74.81      .1       0
   90.35      .1       0   202.6    .045       0   213.9      .1       0
  247.91     .12       0  304.63    .055       0
#XS Ineff= 2 , 0
          178.91 2063.64
Permanent Ineff=
       F       F
Bank Sta=202.6,213.9
XS Rating Curve= 0 ,0
Exp/Cntr(USF)=0,0
Exp/Cntr=0.3,0.1

Type RM Length L Ch R = 1 ,1553    ,239.8,239.9,239.9
XS GIS Cut Line= 2
2200546.43461441326209.0613232162200842.90144222326490.155355435
#Sta/Elev= 30
       0 2071.96     4.4 2067.63    12.2 2062.08      18 2059.63    22.5 2058.83
    34.8 2059.23    42.4 2058.97    58.7 2060.31    85.8 2059.68     112 2059.77
   123.6 2060.98   140.1 2060.75   163.1 2062.32   167.2 2061.77   179.3 2058.55
   192.1 2058.49   203.4  2057.5   214.1  2057.9     223 2056.31   230.5 2055.27
     235 2056.25     235 2056.26   239.7 2057.72   244.3 2061.61   248.6 2062.32
   262.9 2061.99   286.1 2062.79   325.4 2066.28   352.6    2068   408.5 2068.66
#Mann= 8 ,-1 , 0
       0      .1       0   11.41     .06       0   15.42      .1       0
  134.62      .1       0     223    .045       0     235      .1       0
  343.17    .055       0  381.02      .1       0
#XS Ineff= 2 , 0
          161.81 2062.17
Permanent Ineff=
       F       F
Bank Sta=223,235
XS Rating Curve= 0 ,0
Exp/Cntr(USF)=0,0
Exp/Cntr=0.3,0.1

Type RM Length L Ch R = 1 ,1313    ,193,194.5,194.9
XS GIS Cut Line= 2
 2200406.3190469326356.2834612332200713.53411406 326643.60505629
#Sta/Elev= 30
       0 2085.86    16.6 2071.55    25.6 2064.45    35.6 2058.05    40.4  2056.1
      50 2055.28    58.3 2056.04    70.5 2055.66    83.8 2056.78   102.9 2057.06
     114 2057.81   126.9 2057.29   162.7 2058.21   169.7 2057.22     179  2053.6
   189.3 2052.35   202.2 2051.74   204.5 2052.19   209.7 2057.24   216.1  2058.9
   225.4  2058.3   260.2 2058.07   271.8 2058.97   288.1 2058.13     322 2058.05
   339.2 2059.28   357.4 2061.95   380.4 2064.54   408.8 2066.23   420.6 2067.62
#Mann= 5 ,-1 , 0
       0     .06       0  106.16      .1       0   189.3    .045       0
   204.5      .1       0  225.67      .1       0
#XS Ineff= 2 , 0
          162.83 2058.27
Permanent Ineff=
       F       F
Bank Sta=189.3,204.5
XS Rating Curve= 0 ,0
Exp/Cntr(USF)=0,0
Exp/Cntr=0.3,0.1

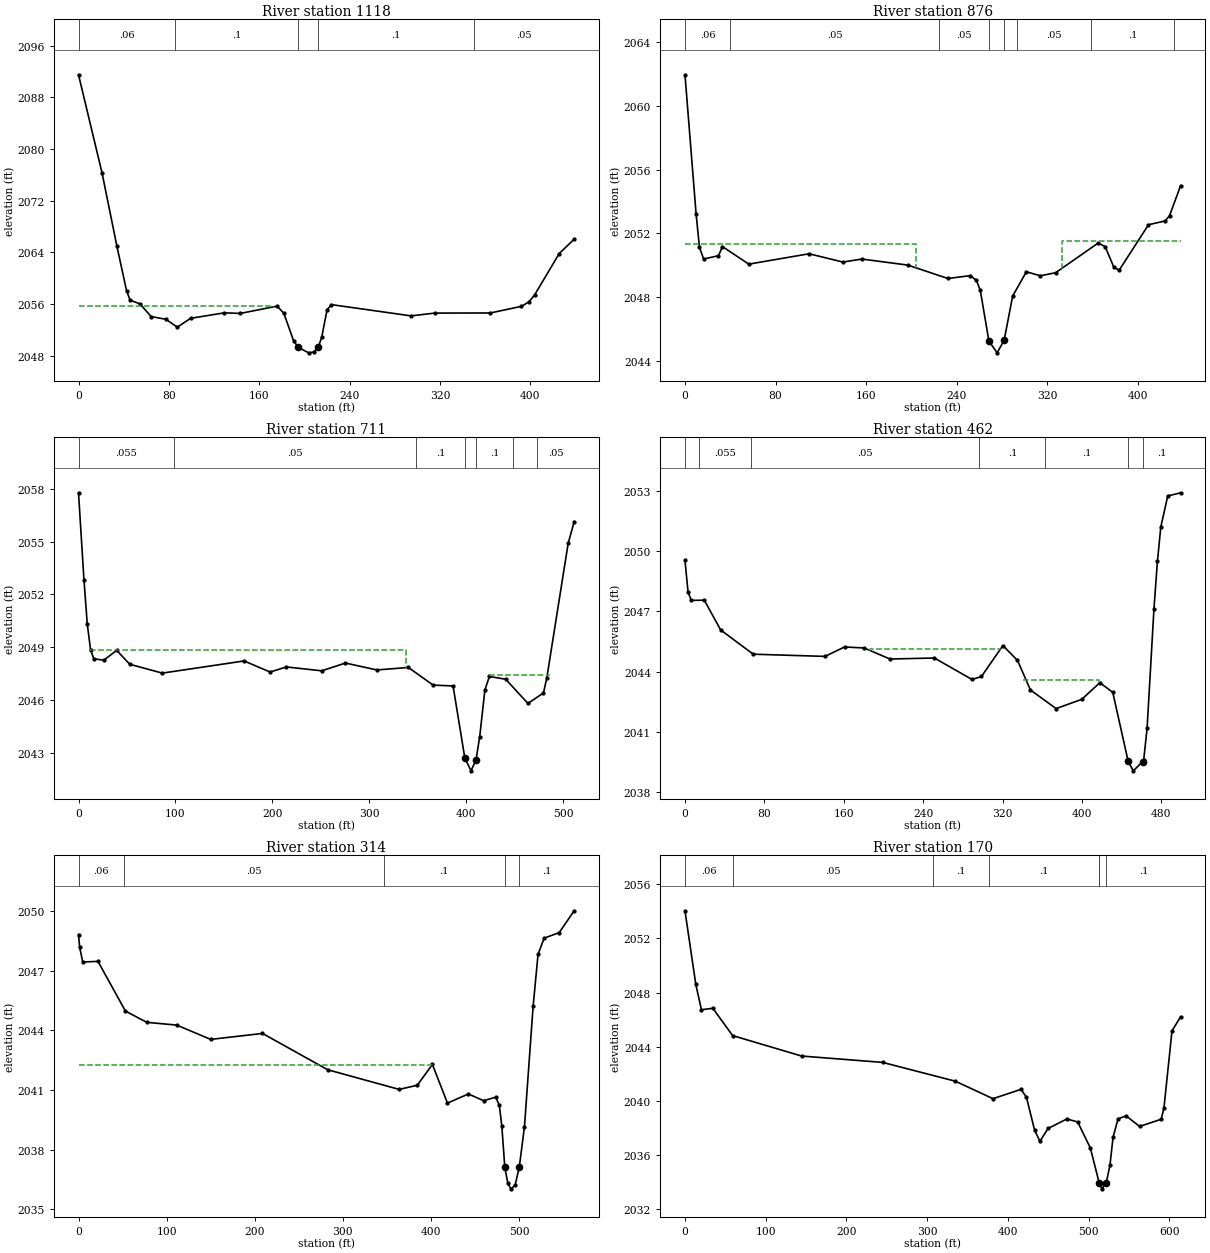
Type RM Length L Ch R = 1 ,1118    ,244,242.5,241
XS GIS Cut Line= 2
2200277.76314645326469.9708060412200566.29964678326800.754826725
#Sta/Elev= 30
       0  2091.5    20.8 2076.34      34 2064.97    42.5 2058.11    45.7 2056.61
    54.3 2056.06    64.3 2054.09    77.4 2053.66    87.5 2052.44    99.2 2053.81
   129.1 2054.66   143.3 2054.57   175.9  2055.7   181.8 2054.59   190.5 2050.32
   194.5 2049.33   203.8 2048.47   208.4  2048.6   212.3 2049.34   215.4 2050.91
   220.1 2055.14     224 2055.93   294.5 2054.19   315.4 2054.62   364.7 2054.64
   392.1 2055.66   398.7 2056.34   403.8 2057.41   425.6 2063.82   438.9 2066.06
#Mann= 5 ,-1 , 0
       0     .06       0   85.19      .1       0   194.5    .045       0
   212.3      .1       0  349.84     .05       0
#XS Ineff= 2 , 0
          172.17 2055.65
Permanent Ineff=
       F       F
Bank Sta=194.5,212.3
XS Rating Curve= 0 ,0
Exp/Cntr(USF)=0,0
Exp/Cntr=0.3,0.1

Type RM Length L Ch R = 1 ,876     ,164.1,164.9,165.2
XS GIS Cut Line= 3
2200124.60483991326564.528829409 2200151.4258654326723.539194816
2200373.59098037326888.422374738
#Sta/Elev= 30
       0 2061.94     9.8 2053.24    12.8 2051.12    16.5 2050.39    29.6  2050.6
    33.1 2051.17    56.4 2050.07   109.6 2050.72   139.6  2050.2   156.2 2050.39
   196.9 2050.01   232.3 2049.17     252 2049.35   257.5 2049.05   260.9 2048.43
   268.5 2045.25   275.8 2044.51     2822045.308   289.5 2048.07   301.6 2049.59
     314 2049.34   327.4 2049.53     365 2051.39   371.2 2051.17     379 2049.86
   383.7  2049.7   409.5 2052.54   424.3 2052.78   428.1 2053.11   437.9 2054.99
#Mann= 8 ,-1 , 0
       0     .06       0   39.77     .05       0  224.81     .05       0
   268.5    .045       0     282      .1       0  293.34     .05       0
   358.6      .1       0  432.02     .05       0
#XS Ineff= 2 , 0
          203.96 2051.32  332.66         2051.51
Permanent Ineff=
       F       F
Bank Sta=268.5,282
XS Rating Curve= 0 ,0
Exp/Cntr(USF)=0,0
Exp/Cntr=0.3,0.1

Type RM Length L Ch R = 1 ,711     ,245.4,248.4,252.1
XS GIS Cut Line= 3
2199988.47360629326575.2812561182200049.88912605326832.739084312
  2200230.709472327000.276701639
#Sta/Elev= 30
       0 2057.77     5.6 2052.84       9 2050.33    12.4 2048.86    15.7 2048.35
    25.9 2048.26    39.4 2048.82    52.9 2048.03    86.4 2047.53   170.8 2048.22
   197.6 2047.59   214.4 2047.88   250.8 2047.66   275.3  2048.1   307.7 2047.71
   340.2 2047.85   365.7 2046.85   386.3  2046.8   398.42042.717   404.8 2041.98
     410 2042.61   413.8 2043.93   419.1 2046.57   423.8 2047.34   440.6 2047.18
   463.5 2045.81   479.5  2046.4   482.9 2047.23     505 2054.89   511.2 2056.13
#Mann= 7 ,-1 , 0
       0    .055       0   98.15     .05       0   348.2      .1       0
   398.4    .045       0     410      .1       0  447.71      .1       0
  473.23     .05       0
#XS Ineff= 2 ,-1
   11.36  337.85 2048.87  424.07  486.53 2047.43
Permanent Ineff=
       F       F
Bank Sta=398.4,410
XS Rating Curve= 0 ,0
Exp/Cntr(USF)=0,0
Exp/Cntr=0.3,0.1

Type RM Length L Ch R = 1 ,462     ,148.5,148.6,148.8
XS GIS Cut Line= 3
2199873.34065224326633.4662247322199884.17350427326848.065384592
2199974.25860284327118.017663031
#Sta/Elev= 30
       0 2049.54     3.1 2047.96     6.4 2047.55    19.5 2047.56    35.9 2046.08
    68.8 2044.87   141.1 2044.76   160.8 2045.23   180.5 2045.18   206.6 2044.63
   251.3 2044.68   289.3 2043.61   298.8 2043.76   320.4  2045.3   335.1 2044.56
   348.1 2043.09     374 2042.16   399.8 2042.62   418.1 2043.45   431.1 2042.97
   446.6 2039.54   451.8 2039.06   461.12039.512   462.3 2039.61   465.7 2041.18
   472.6 2047.11   476.1 2049.49   479.5  2051.2   486.5 2052.75   499.5 2052.91
#Mann= 7 ,-1 , 0
       0     .06       0   14.36    .055       0   66.65     .05       0
  296.77      .1       0   363.3      .1       0   446.6    .045       0
   461.1      .1       0
#XS Ineff= 2 ,-1
  186.91  318.61 2045.14  340.69  417.19 2043.56
Permanent Ineff=
       F       F
Bank Sta=446.6,461.1
XS Rating Curve= 0 ,0
Exp/Cntr(USF)=0,0
Exp/Cntr=0.3,0.1

Type RM Length L Ch R = 1 ,314     ,141.1,144.1,145.7
XS GIS Cut Line= 3
2199862.62315628 326641.821003942199763.94931581326938.817369883
2199835.97201288327177.715152685
#Sta/Elev= 30
       0 2048.83     1.3 2048.19     4.8 2047.45    22.1 2047.48    53.2 2044.98
    77.4 2044.41   111.5 2044.27     150 2043.55   208.8 2043.85   282.8 2042.02
   363.9 2041.03   384.5 2041.24   401.6 2042.29   418.7 2040.34   442.4  2040.8
   459.8 2040.46   473.5 2040.64   477.6 2040.22   480.4 2039.18   483.8  2037.1
   487.3 2036.29   490.7 2036.02   495.5  2036.2   500.3 2037.14   506.1 2039.16
   515.9 2045.21   521.5 2047.83   528.4 2048.65   545.5 2048.93   562.5 2050.03
#Mann= 5 ,-1 , 0
       0     .06       0   51.72     .05       0  346.33      .1       0
   483.8    .045       0   500.3      .1       0
#XS Ineff= 2 , 0
          402.13 2042.28
Permanent Ineff=
       F       F
Bank Sta=483.8,500.3
XS Rating Curve= 0 ,0
Exp/Cntr(USF)=0,0
Exp/Cntr=0.3,0.1

Type RM Length L Ch R = 1 ,170     ,122.8,122.9,122.9
XS GIS Cut Line= 3
2199840.50197254326650.2047706962199695.79333701327036.016837375
2199658.77444492327234.292327187
#Sta/Elev= 30
       0 2054.04    13.4  2048.6    20.4 2046.73    34.5 2046.84      59 2044.82
   144.4 2043.31   244.7 2042.84   334.9 2041.45   381.4 2040.16   416.2 2040.85
   422.9 2040.26   432.9 2037.85   439.5 2037.01   449.6 2037.96   472.9 2038.66
   486.3 2038.44     502 2036.52   512.6 2034.02     513 2033.91   516.3  2033.5
   521.7 2033.95   526.3 2035.25   530.1  2037.3   536.3 2038.67   546.3 2038.89
     563 2038.11   589.7 2038.64   593.1 2039.46   603.1 2045.17   613.8 2046.21
#Mann= 7 ,-1 , 0
       0     .06       0   59.65     .05       0  306.98      .1       0
  376.12      .1       0   512.6    .045       0     513    .045       0
   521.7      .1       0
#XS Ineff= 1 ,-1
  545.65  598.64 2038.85
Permanent Ineff=
       F
Bank Sta=513,521.7
XS Rating Curve= 0 ,0
Exp/Cntr=0.5,0.3

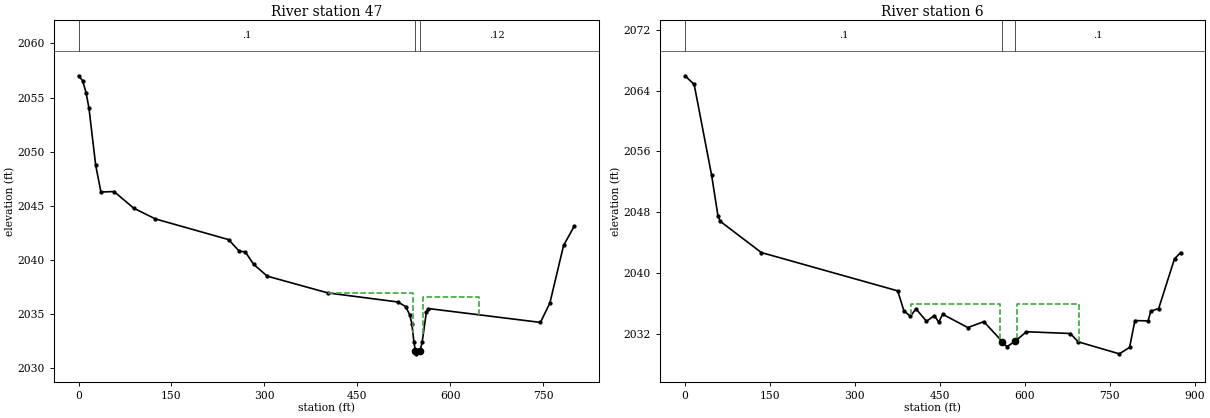
Type RM Length L Ch R = 1 ,47      ,41.2,41.2,41.2
XS GIS Cut Line= 6
2199830.13131669326654.4484484172199632.24744341326896.917966735
2199560.80933351327092.2392744092199551.12245613327141.744649437
2199530.05398167327313.6203100052199561.36057008327359.283008431
#Sta/Elev= 30
       0 2057.01     6.5 2056.57    12.2 2055.45    16.9 2054.01    27.7 2048.76
    36.2 2046.28    57.3 2046.33    89.1 2044.79   124.1  2043.8   242.3 2041.89
   259.4 2040.82   269.1 2040.76   282.7 2039.61   304.5 2038.52   402.5 2036.97
   515.1 2036.14     528 2035.71   534.7 2034.93     538 2034.11   541.3  2032.4
   543.8 2031.64   544.7 2031.35   551.4 2031.64   554.7 2032.48   561.4  2035.2
   564.7 2035.53   745.5 2034.25   760.7 2036.04   782.8 2041.35   799.9 2043.12
#Mann= 3 , 0 , 0
       0      .1       0   543.8    .045       0   551.4     .12       0
#XS Ineff= 2 ,-1
  402.41  539.69    2037  556.34  646.34 2036.59
Permanent Ineff=
       F       F
Bank Sta=543.8,551.4
XS Rating Curve= 0 ,0
Exp/Cntr(USF)=0,0
Exp/Cntr=0.5,0.3

Type RM Length L Ch R = 1 ,6       ,11,11,11
XS GIS Cut Line= 6
2199821.81711343326644.1029943072199619.79482444326888.296922828
2199495.08515637327154.0286664852199486.91167188 327224.56361517
2199499.72672151327327.0880434232199563.22525793327391.125267593
#Sta/Elev= 30
       0 2065.94    16.2 2064.81    47.1 2052.85    58.3 2047.53    62.6 2046.81
   134.8 2042.73   375.5  2037.7   386.6 2035.07   398.1 2034.36   407.9 2035.34
   426.4  2033.7   440.1 2034.45   448.1 2033.59   454.9 2034.63   499.4 2032.88
   527.6 2033.66   560.12031.043   568.4 2030.36   583.2  2031.1   602.8 2032.33
   680.6  2032.1   694.1 2031.01   766.8 2029.43     785 2030.28   794.4  2033.8
   817.7 2033.75   822.3 2035.02   836.3 2035.38   864.3 2041.91   875.1 2042.72
#Mann= 3 , 0 , 0
       0      .1       0   560.1    .045       0   583.2      .1       0
#XS Ineff= 2 ,-1
  399.33   556.2 2036.02   586.7  694.94 2035.98
Permanent Ineff=
       F       F
Bank Sta=560.1,583.2
XS Rating Curve= 0 ,0
Exp/Cntr(USF)=0,0
Exp/Cntr=0.5,0.3
LCMann Table=0

Chan Stop Cuts=-1
Use User Specified Reach Order=0
Composite Channel Slope=5